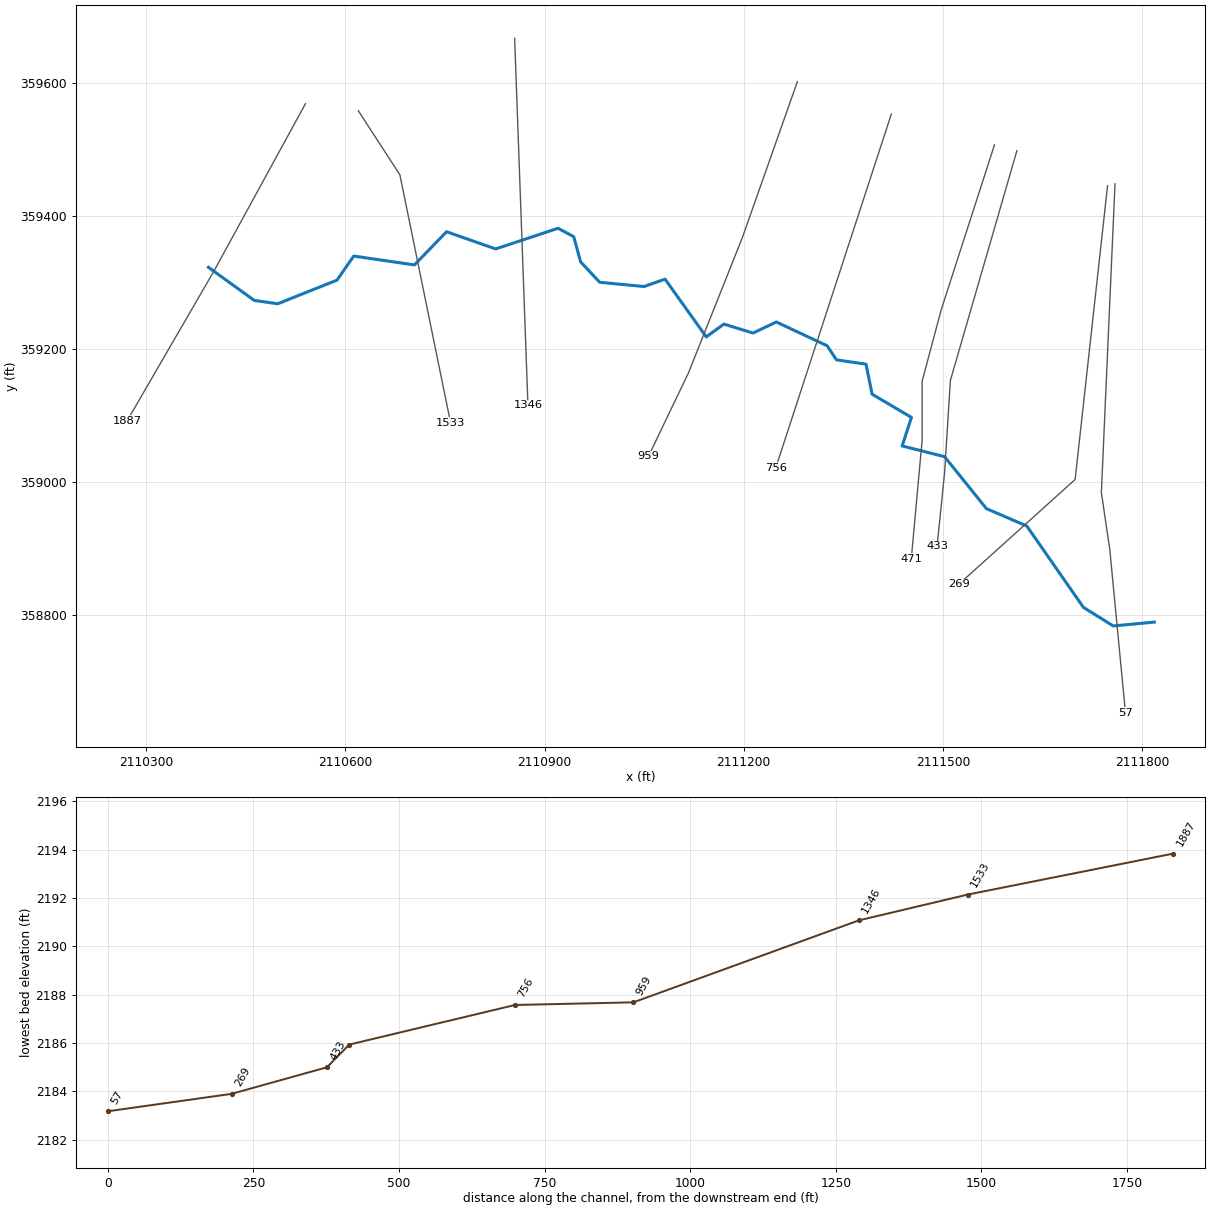
--- SNKNGCKT3.prj (project) ---

Proj Title=SNKNGCKT3
Current Plan=p01
Default Exp/Contr=0.3,0.1
English Units
Geom File=g01
Flow File=f01
Plan File=p01
Y Axis Title=Elevation
X Axis Title(PF)=Main Channel Distance
X Axis Title(XS)=Station
BEGIN DESCRIPTION:
Stream Name- Sinking Creek Tributary 3
Flood Zone: Zone A
Greenbrier County, WV
County-Wide Study
WVDHSEM-2018-3, Flood Risk Project
HEC-RAS Version: 5.0.7
General Notes:
For the Hydrology Regression was used.
END DESCRIPTION:
DSS Export Rating Curves= 0
DSS Export Rating Curve Sorted= 0
DSS Export Volume Flow Curves= 0
DXF Filename=SNKNGCKT3.F2.
DXF OffsetX= 0
DXF OffsetY= 0
DXF ScaleX= 1
DXF ScaleY= 10

--- SNKNGCKT3.p01 (plan) ---

Plan Title=Floodplain
Program Version=5.07
Short Identifier=Floodplain
Geom File=g01
Flow File=f01
Subcritical Flow
K Sum by GR= 0
Std Step Tol= 0.01
Critical Tol= 0.01
Num of Std Step Trials= 20
Max Error Tol= 0.3
Flow Tol Ratio= 0.001
Split Flow NTrial= 30
Split Flow Tol= 0.02
Split Flow Ratio= 0.02
Log Output Level= 0
Friction Slope Method= 1
Unsteady Friction Slope Method= 2
Unsteady Bridges Friction Slope Method= 1
Parabolic Critical Depth
Global Vel Dist= 0 , 0 , 0
Global Log Level= 0
CheckData=True
Encroach Param=-1 ,0,0, 0
Computation Interval=1MIN
Output Interval=1HOUR
Instantaneous Interval=1HOUR
Mapping Interval=1HOUR
Computation Time Step Use Courant=        0
Computation Time Step Use Time Series=    0
Computation Time Step Count To Double=0
Computation Time Step Max Doubling=0
Computation Time Step Max Halving=0
Computation Time Step Residence Courant=0
Run HTab= 0
Run UNet= 0
Run Sediment= 0
Run PostProcess= 0
Run WQNet= 0
Run RASMapper= 0
UNET Theta= 1
UNET Theta Warmup= 1
UNET ZTol= 0.02
UNET ZSATol= 0.02
UNET MxIter= 20
UNET Max Iter WO Improvement= 0
UNET MaxInSteps= 0
UNET DtIC= 0
UNET DtMin= 0
UNET MaxCRTS= 20
UNET WFStab= 2
UNET SFStab= 1
UNET WFX= 1
UNET SFX= 1
UNET 1D Methodology=Finite Difference
UNET DSS MLevel= 4
UNET Pardiso=0
UNET DZMax Abort= 100
UNET Use Existing IB Tables=-1
UNET Froude Reduction=False
UNET Froude Limit= 0.8
UNET Froude Power= 4
UNET D1 Cores= 0
UNET D2 Coriolis=0
UNET D2 Cores= 0
UNET D2 Theta= 1
UNET D2 Theta Warmup= 1
UNET D2 Z Tol= 0.01
UNET D2 Volume Tol= 0.01
UNET D2 Max Iterations= 20
UNET D2 Equation= 0
UNET D2 RampUpFraction=0.1
UNET D2 TimeSlices= 1
UNET D2 BCVolumeCheck=0
UNET D1D2 MaxIter= 0
UNET D1D2 ZTol=0.01
UNET D1D2 QTol=0.1
UNET D1D2 MinQTol=1
Write IC File= 0
Write IC File at Fixed DateTime=0
Write IC File at Sim End=0
Echo Input=False
Echo Parameters=False
Echo Output=False
Write Detailed= 0
HDF Write Warmup=0
HDF Write Time Slices=0
HDF Flush=0
HDF Face Node Velocities=0
HDF Compression= 1
HDF Chunk Size= 1
HDF Spatial Parts= 1
HDF Use Max Rows=0
HDF Fixed Rows= 1
Calibration Method= 0
Calibration Iterations= 20
Calibration Max Change=0.05
Calibration Tolerance=0.2
Calibration Maximum=1.5
Calibration Minimum=0.5
Calibration Optimization Method= 1
WQ AD Non Conservative
WQ ULTIMATE=-1
WQ Max Comp Step=1HOUR
WQ Output Interval=15MIN
WQ Output Selected Increments= 0
WQ Output face flow=0
WQ Output face velocity=0
WQ Output face area=0
WQ Output face dispersion=0
WQ Output cell volume=0
WQ Output cell surface area=0
WQ Output cell continuity=0
WQ Output cumulative cell continuity=0
WQ Output face conc=0
WQ Output face dconc_dx=0
WQ Output face courant=0
WQ Output face peclet=0
WQ Output face adv mass=0
WQ Output face disp mass=0
WQ Output cell mass=0
WQ Output cell source sink temp=0
WQ Output nsm pathways=0
WQ Output nsm derived pathways=0
WQ Output MaxMinRange=-1
WQ Daily Max Min Mean=-1
WQ Daily Range=0
WQ Daily Time=0
WQ Create Restart=0
WQ Fixed Restart=0
WQ System Summary=0
WQ Write To DSS=0
WQ Use Fixed Temperature=0
Sorting and Armoring Iterations= 10
XS Update Threshold= 0.02
Bed Roughness Predictor= 0
Hydraulics Update Threshold= 0.02
Energy Slope Method= 1
Volume Change Method= 1
Sediment Retention Method= 0
XS Weighting Method= 0
Number of US Weighted Cross Sections= 1
Number of DS Weighted Cross Sections= 1
Upstream XS Weight=0
Main XS Weight=1
Downstream XS Weight=0
Number of DS XS's Weighted with US Boundary= 1
Upstream Boundary Weight= 1
Weight of XSs Associated with US Boundary= 0
Number of US XS's Weighted with DS Boundary= 1
Downstream Boundary Weight= 0.5
Weight of XSs Associated with DS Boundary= 0.5
Percentile Method= 0
Sediment Output Level= 3
Mass or Volume Output= 0
Output Increment Type= 1
Profile and TS Output Increment= 1
XS Output Flag= 0
XS Output Increment= 10
Write Gradation File= 0
Read Gradation Hotstart= 0
Write HDF5 File= 1
Write Binary Output= 1
Write DSS Sediment File= 0
SV Curve= 0
Specific Gage Flag= 0

--- SNKNGCKT3.f01 (steady flow) ---

Flow Title=Flow
Program Version=5.07
Number of Profiles= 6
Profile Names=f1p,f10p,f4p,f2p,f02p,f1pplus
River Rch & RM=SNKNGCKT3,Main            ,1887
     154    77.6     106     129     221     228
River Rch & RM=SNKNGCKT3,Main            ,756
     172    86.8     118     144     246     255
Boundary for River Rch & Prof#=FLYNNCK,Main            , 1
Up Type= 0
Dn Type= 3
Dn Slope=0.009659
Boundary for River Rch & Prof#=FLYNNCK,Main            , 2
Up Type= 0
Dn Type= 3
Dn Slope=0.009659
Boundary for River Rch & Prof#=FLYNNCK,Main            , 3
Up Type= 0
Dn Type= 3
Dn Slope=0.009659
Boundary for River Rch & Prof#=FLYNNCK,Main            , 4
Up Type= 0
Dn Type= 3
Dn Slope=0.009659
Boundary for River Rch & Prof#=FLYNNCK,Main            , 5
Up Type= 0
Dn Type= 3
Dn Slope=0.009659
Boundary for River Rch & Prof#=FLYNNCK,Main            , 6
Up Type= 0
Dn Type= 3
Dn Slope=0.009659
Boundary for River Rch & Prof#=HUGHRTCK,Main            , 1
Up Type= 0
Dn Type= 3
Dn Slope=0.002151
Boundary for River Rch & Prof#=HUGHRTCK,Main            , 2
Up Type= 0
Dn Type= 3
Dn Slope=0.002151
Boundary for River Rch & Prof#=HUGHRTCK,Main            , 3
Up Type= 0
Dn Type= 3
Dn Slope=0.002151
Boundary for River Rch & Prof#=HUGHRTCK,Main            , 4
Up Type= 0
Dn Type= 3
Dn Slope=0.002151
Boundary for River Rch & Prof#=HUGHRTCK,Main            , 5
Up Type= 0
Dn Type= 3
Dn Slope=0.002151
Boundary for River Rch & Prof#=HUGHRTCK,Main            , 6
Up Type= 0
Dn Type= 3
Dn Slope=0.002151
Boundary for River Rch & Prof#=HUGHRTCKT1,Main            , 1
Up Type= 0
Dn Type= 3
Dn Slope=0.008324
Boundary for River Rch & Prof#=HUGHRTCKT1,Main            , 2
Up Type= 0
Dn Type= 3
Dn Slope=0.008324
Boundary for River Rch & Prof#=HUGHRTCKT1,Main            , 3
Up Type= 0
Dn Type= 3
Dn Slope=0.008324
Boundary for River Rch & Prof#=HUGHRTCKT1,Main            , 4
Up Type= 0
Dn Type= 3
Dn Slope=0.008324
Boundary for River Rch & Prof#=HUGHRTCKT1,Main            , 5
Up Type= 0
Dn Type= 3
Dn Slope=0.008324
Boundary for River Rch & Prof#=HUGHRTCKT1,Main            , 6
Up Type= 0
Dn Type= 3
Dn Slope=0.008324
Boundary for River Rch & Prof#=SNKNGCKT1,Main            , 1
Up Type= 0
Dn Type= 3
Dn Slope=0.003593
Boundary for River Rch & Prof#=SNKNGCKT1,Main            , 2
Up Type= 0
Dn Type= 3
Dn Slope=0.003593
Boundary for River Rch & Prof#=SNKNGCKT1,Main            , 3
Up Type= 0
Dn Type= 3
Dn Slope=0.003593
Boundary for River Rch & Prof#=SNKNGCKT1,Main            , 4
Up Type= 0
Dn Type= 3
Dn Slope=0.003593
Boundary for River Rch & Prof#=SNKNGCKT1,Main            , 5
Up Type= 0
Dn Type= 3
Dn Slope=0.003593
Boundary for River Rch & Prof#=SNKNGCKT1,Main            , 6
Up Type= 0
Dn Type= 3
Dn Slope=0.003593
Boundary for River Rch & Prof#=SNKNGCKT2,Main            , 1
Up Type= 0
Dn Type= 3
Dn Slope=0.006517
Boundary for River Rch & Prof#=SNKNGCKT2,Main            , 2
Up Type= 0
Dn Type= 3
Dn Slope=0.006517
Boundary for River Rch & Prof#=SNKNGCKT2,Main            , 3
Up Type= 0
Dn Type= 3
Dn Slope=0.006517
Boundary for River Rch & Prof#=SNKNGCKT2,Main            , 4
Up Type= 0
Dn Type= 3
Dn Slope=0.006517
Boundary for River Rch & Prof#=SNKNGCKT2,Main            , 5
Up Type= 0
Dn Type= 3
Dn Slope=0.006517
Boundary for River Rch & Prof#=SNKNGCKT2,Main            , 6
Up Type= 0
Dn Type= 3
Dn Slope=0.006517
Boundary for River Rch & Prof#=SNKNGCKT3,Main            , 1
Up Type= 0
Dn Type= 3
Dn Slope=0.00548
Boundary for River Rch & Prof#=SNKNGCKT3,Main            , 2
Up Type= 0
Dn Type= 3
Dn Slope=0.00548
Boundary for River Rch & Prof#=SNKNGCKT3,Main            , 3
Up Type= 0
Dn Type= 3
Dn Slope=0.00548
Boundary for River Rch & Prof#=SNKNGCKT3,Main            , 4
Up Type= 0
Dn Type= 3
Dn Slope=0.00548
Boundary for River Rch & Prof#=SNKNGCKT3,Main            , 5
Up Type= 0
Dn Type= 3
Dn Slope=0.00548
Boundary for River Rch & Prof#=SNKNGCKT3,Main            , 6
Up Type= 0
Dn Type= 3
Dn Slope=0.00548
Boundary for River Rch & Prof#=SNKNGCKT4,Main            , 1
Up Type= 0
Dn Type= 3
Dn Slope=0.00461
Boundary for River Rch & Prof#=SNKNGCKT4,Main            , 2
Up Type= 0
Dn Type= 3
Dn Slope=0.00461
Boundary for River Rch & Prof#=SNKNGCKT4,Main            , 3
Up Type= 0
Dn Type= 3
Dn Slope=0.00461
Boundary for River Rch & Prof#=SNKNGCKT4,Main            , 4
Up Type= 0
Dn Type= 3
Dn Slope=0.00461
Boundary for River Rch & Prof#=SNKNGCKT4,Main            , 5
Up Type= 0
Dn Type= 3
Dn Slope=0.00461
Boundary for River Rch & Prof#=SNKNGCKT4,Main            , 6
Up Type= 0
Dn Type= 3
Dn Slope=0.00461
Boundary for River Rch & Prof#=STONYRN,Main            , 1
Up Type= 0
Dn Type= 3
Dn Slope=0.005293
Boundary for River Rch & Prof#=STONYRN,Main            , 2
Up Type= 0
Dn Type= 3
Dn Slope=0.005293
Boundary for River Rch & Prof#=STONYRN,Main            , 3
Up Type= 0
Dn Type= 3
Dn Slope=0.005293
Boundary for River Rch & Prof#=STONYRN,Main            , 4
Up Type= 0
Dn Type= 3
Dn Slope=0.005293
Boundary for River Rch & Prof#=STONYRN,Main            , 5
Up Type= 0
Dn Type= 3
Dn Slope=0.005293
Boundary for River Rch & Prof#=STONYRN,Main            , 6
Up Type= 0
Dn Type= 3
Dn Slope=0.005293
DSS Import GetInterval= 0
DSS Import GetPeak= 0
DSS Import FillOption= 0

--- SNKNGCKT3.g01 (geometry) ---

Geom Title=Geometry
Program Version=5.07

River Reach=SNKNGCKT3       ,Main
Reach XY= 30
2110393.65510805359323.1570724842110462.58410406359273.374035567
2110497.91408588359268.2369067222110587.28497013359303.853961483
2110612.51556273359340.0674717282110703.93550586359326.752965291
2110752.31679231359376.6818998162110826.28547639359350.792843983
2110920.22623339359381.8597109762110943.89613356359369.284932971
2110954.28193955359331.3886833042110983.04041222359300.592156976
2111049.90674831359294.2237313992111081.42965114359305.368394136
2111143.52007814359218.4417307232111170.07940821359237.683490142
2111213.92479298359224.2146850682111249.17308205359240.835714817
2111325.68736473359205.0142641372111339.72933139359183.808269814
2111384.24925546359177.3994899842111393.31813496359132.225367725
 2111452.6382263359097.2638234792111438.59625964359054.278345138
2111502.50164364359038.2301488972111565.56418155358959.964885473
2111626.41642205358933.7841635642111711.68003106358811.372662976
2111756.61137164358783.4232438062111818.46131356358789.183402896

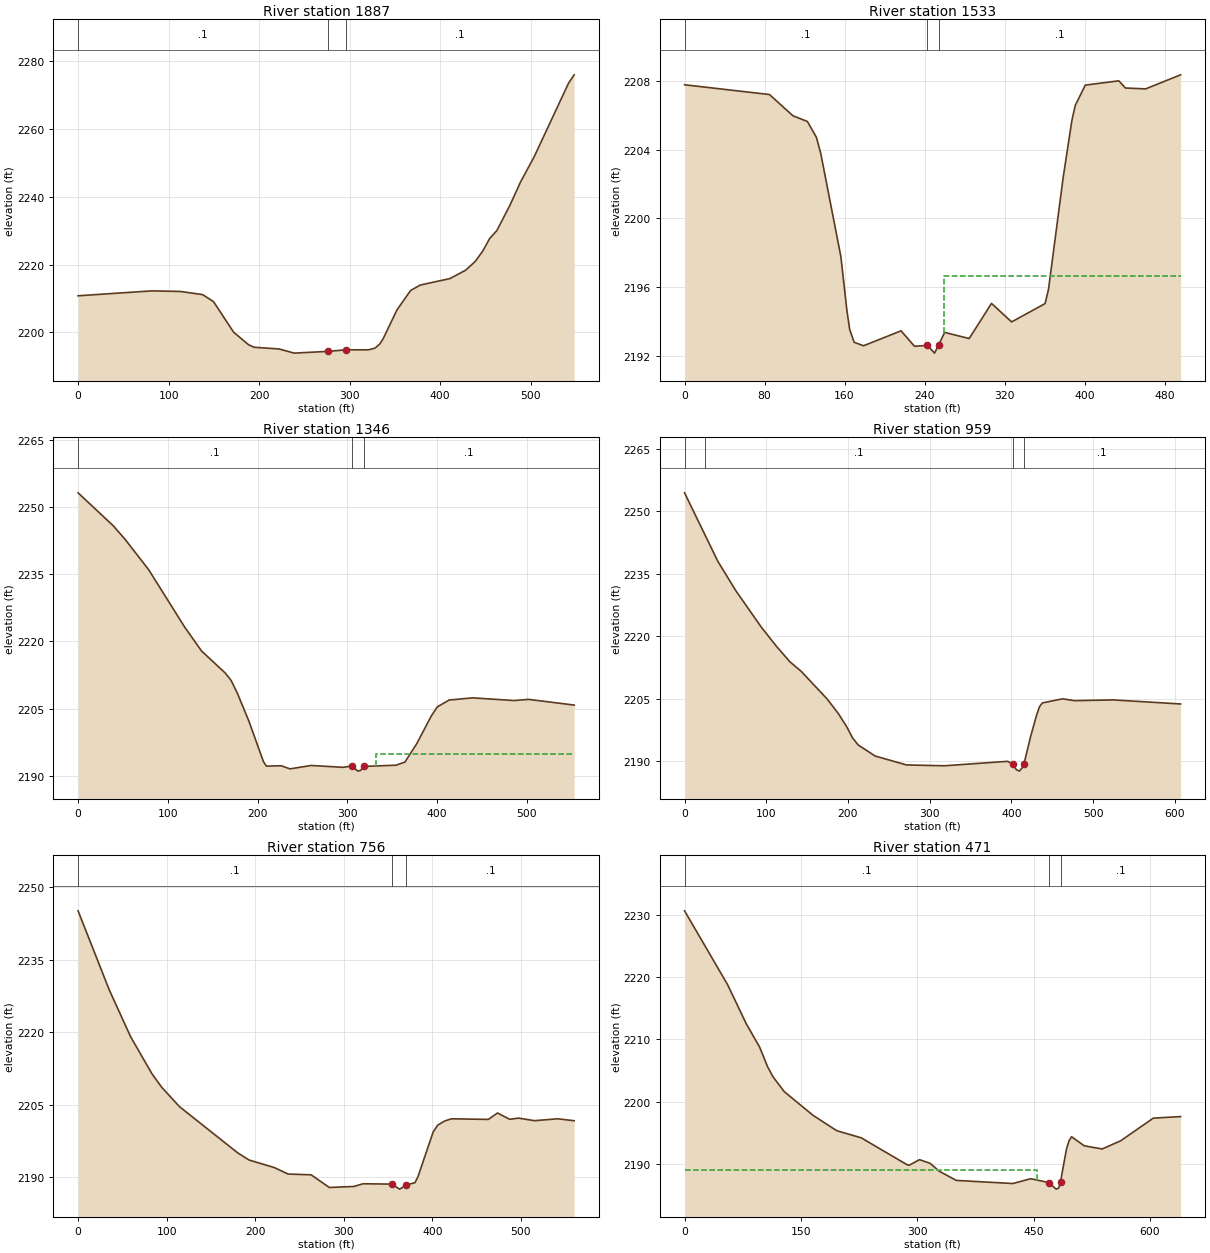
Type RM Length L Ch R = 1 ,1887    ,343.2,353.5,357.5
XS GIS Cut Line= 3
 2110539.7955638359569.3399790672110402.33389647359318.189890817
2110271.01887038359091.882928729
#Sta/Elev= 30
       0 2210.78    81.6 2212.23   113.3 2212.05   137.5 2211.13   149.6 2209.06
   171.8 2200.03   188.2 2196.34   194.3 2195.58   222.1 2195.06   238.8 2193.84
   276.32194.368  296.312194.822   320.9 2194.81   328.1 2195.34   333.3 2196.53
   337.1 2198.15   352.3 2206.62   367.4 2212.36   378.1 2213.96   410.8 2215.86
   428.1 2218.34   438.6 2220.89   447.1 2224.01   454.7 2227.71   462.6 2230.04
     477 2237.49   488.8  2244.4     504 2251.93   541.9 2273.63     548 2276.05
#Mann= 3 ,-1 , 0
       0      .1       0   276.3    .045       0  296.31      .1       0
Bank Sta=276.3,296.31
XS Rating Curve= 0 ,0
Exp/Cntr=0.3,0.1

Type RM Length L Ch R = 1 ,1533    ,179,187.1,175.6
XS GIS Cut Line= 3
2110619.39907914359558.7638847232110682.03248405359462.308368981
2110758.44538897359089.012527645
#Sta/Elev= 30
       0 2207.79    84.9 2207.22   108.4 2205.98   122.8 2205.65   131.8 2204.73
   136.2 2203.78   156.3 2197.77   162.3 2194.64   165.1 2193.52   169.6 2192.77
     179 2192.57   216.5 2193.44   229.9 2192.54   242.9 2192.59     250 2192.14
   254.1 2192.63   260.1 2193.35   284.6 2192.99   306.9 2195.04     327 2193.96
   360.5 2195.03   363.9 2195.86   378.6 2202.39   387.3 2205.71   390.7 2206.59
   400.7 2207.77   434.2 2208.02   440.9  2207.6     461 2207.55     496 2208.37
#Mann= 3 , 0 , 0
       0      .1       0   242.9    .045       0   254.1      .1       0
#XS Ineff= 2 , 0
                          259.76         2196.61
Permanent Ineff=
       F       F
Bank Sta=242.9,254.1
XS Rating Curve= 0 ,0
Exp/Cntr=0.3,0.1

Type RM Length L Ch R = 1 ,1346    ,383.9,386.8,376.6
XS GIS Cut Line= 2
2110854.90090472359667.7462783162110874.94384363359115.318577394
#Sta/Elev= 30
       0 2253.13    39.2 2245.78    52.3 2242.78    78.6    2236   118.9 2223.16
   137.7 2217.83   163.9 2212.97   170.5  2211.3   177.3 2208.53   190.2  2202.3
   206.6 2193.16   209.9 2192.18   226.3 2192.27   236.2 2191.57   259.6 2192.33
   295.3 2191.92   305.1  2192.2   311.7 2191.07     315 2191.25   318.2 2192.12
   354.3 2192.39   364.2 2193.09   377.3 2197.15   393.7  2203.4   400.3 2205.39
   413.4 2206.92   439.7 2207.41   485.7 2206.81   502.1 2207.07   552.8  2205.8
#Mann= 3 ,-1 , 0
       0      .1       0   305.1    .045       0   318.2      .1       0
#XS Ineff= 2 , 0
                          331.75         2194.84
Permanent Ineff=
       F       F
Bank Sta=305.1,318.2
XS Rating Curve= 0 ,0
Exp/Cntr=0.3,0.1

Type RM Length L Ch R = 1 ,959     ,198.2,203.3,195.8
XS GIS Cut Line= 4
2111280.80884555359602.6073009822111198.13250172359368.358097553
2111116.70910814359164.1728103912111056.58094755359038.905672476
#Sta/Elev= 30
       0 2254.39    40.8 2237.95    62.9 2230.89    94.2 2222.12   112.8 2217.53
     129 2213.88   142.9 2211.58   174.6 2204.96   188.2 2201.49   198.6 2198.29
   205.5 2195.69   212.5 2193.95   233.4 2191.29   271.8 2189.16   317.9 2188.96
   395.4 2190.03   401.6 2189.38   406.2 2188.02   409.8 2187.68   413.3  2188.5
  415.082189.498   416.8 2190.46   423.4 2195.83   430.9  2201.1   434.5 2203.13
     438 2204.03   462.7 2205.01   477.1 2204.57   524.4 2204.75   607.2 2203.78
#Mann= 4 ,-1 , 0
       0      .1       0    24.8      .1       0   401.6    .045       0
  415.08      .1       0
Bank Sta=401.6,415.08
XS Rating Curve= 0 ,0
Exp/Cntr=0.3,0.1

Type RM Length L Ch R = 1 ,756     ,272.3,284.6,276.1
XS GIS Cut Line= 2
2111422.36039972 359553.753067972111248.23935689359021.368305981
#Sta/Elev= 30
       0 2245.14    35.2 2228.78    59.3  2219.1    83.3 2211.46    94.4 2208.64
   114.6 2204.61   180.1 2195.09   192.8 2193.61   221.6 2192.03   237.2 2190.69
   263.1 2190.53   283.7 2187.91   311.3 2188.12   321.7 2188.68   354.1 2188.61
   363.1 2187.57   370.82188.436   380.4 2188.91   383.8 2190.17   400.9 2199.38
   406.1 2200.82   413.9 2201.66   421.7 2202.12   463.2 2201.99   473.6 2203.32
   487.4 2202.01   497.2 2202.26   515.4 2201.73   541.4 2202.12   560.1 2201.72
#Mann= 3 ,-1 , 0
       0      .1       0   354.1    .045       0   370.8      .1       0
Bank Sta=354.1,370.8
XS Rating Curve= 0 ,0
Exp/Cntr=0.5,0.3

Type RM Length L Ch R = 1 ,471     ,37.3,38.4,41.2
XS GIS Cut Line= 5
2111577.69145389359507.4044073972111497.52068247359259.375703976
2111468.70938839359151.6462606492111468.70938839359062.706477895
2111452.42464405358884.827568561
#Sta/Elev= 30
       0 2230.62    55.4 2218.79    79.5  2212.5    96.8 2208.74   107.1 2205.58
     114 2203.98   128.6 2201.58   165.7 2197.78   196.3 2195.31   227.8 2194.17
     286 2189.92   289.4 2189.75     303 2190.66   316.6 2190.08   328.5  2188.8
   350.5 2187.33   423.4 2186.83   446.4  2187.6   469.52186.993   479.3 2185.93
   482.6 2186.12  484.812187.107   492.5 2192.34   495.8  2193.7   499.1 2194.34
   515.5 2192.88   538.6 2192.38   562.5  2193.7   604.5 2197.33   639.7 2197.58
#Mann= 3 ,-1 , 0
       0      .1       0   469.5    .045       0  484.81      .1       0
#XS Ineff= 2 , 0
           454.5    2189  499.81            2189
Permanent Ineff=
       F       F
Bank Sta=469.5,484.81
XS Rating Curve= 0 ,0
Exp/Cntr=0.5,0.3

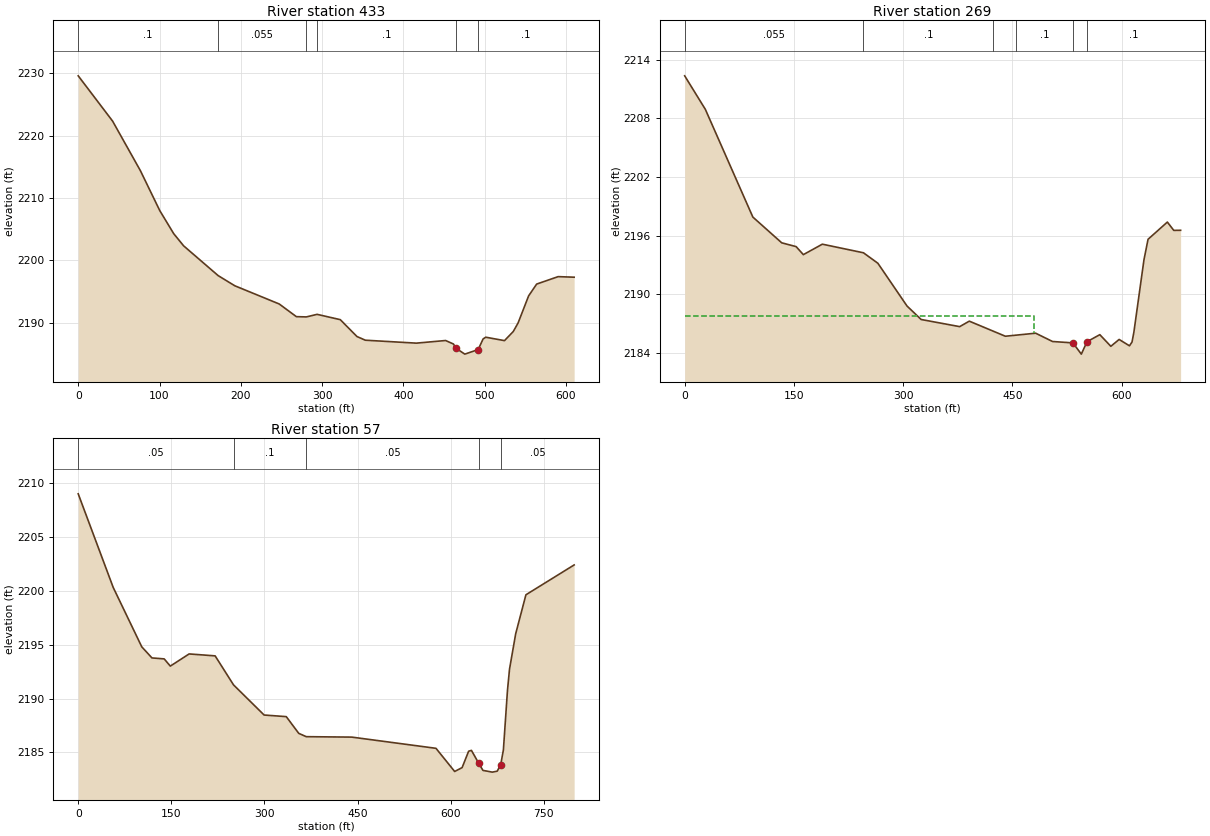
Type RM Length L Ch R = 1 ,433     ,171.6,163.8,152.7
XS GIS Cut Line= 4
2111611.51356472359498.6357241422111511.30018248359152.898882806
2111502.53149922359013.8525729782111491.25724356358903.617557228
#Sta/Elev= 30
       0 2229.56    42.3 2222.31    76.5 2214.37   100.4 2207.96   117.5 2204.28
   129.7 2202.33   172.2 2197.56   192.6 2195.94   247.3 2193.02   268.4 2190.99
   280.7 2190.95   293.9 2191.36   322.4 2190.51   342.9 2187.81   353.2 2187.22
   415.9 2186.75     452 2187.17   461.6 2186.61  465.092185.902   475.6 2184.99
     492 2185.72   498.1 2187.42   501.4  2187.7   524.4 2187.15   535.2 2188.61
   541.2    2190   554.1 2194.32     564 2196.21   590.4  2197.4   610.1 2197.31
#Mann= 6 ,-1 , 0
       0      .1       0   172.2    .055       0   280.7      .1       0
   293.9      .1       0  465.09    .045       0     492      .1       0
Bank Sta=465.09,492
XS Rating Curve= 0 ,0
Exp/Cntr=0.5,0.3

Type RM Length L Ch R = 1 ,269     ,212.3,212.3,212.3
XS GIS Cut Line= 3
2111748.05463022359446.0236246442111699.20039722359003.830939472
2111523.82673222358845.994640976
#Sta/Elev= 30
       0 2212.34    28.4 2208.91    93.6  2197.9   133.2 2195.27     153 2194.88
   162.9 2194.06     189 2195.13   245.4 2194.25   265.2 2193.18   305.2 2188.81
   324.6 2187.43   377.5  2186.7   390.7 2187.26   440.2 2185.72   481.8 2186.03
     505 2185.18   532.9 2185.04   544.5 2183.89   552.3 2185.16   569.9 2185.88
     585 2184.69   596.4 2185.39   610.6 2184.74   614.1 2185.13   616.6 2186.11
   630.5 2193.54   636.1 2195.63   662.6 2197.39   671.4 2196.54   680.8 2196.55
#Mann= 6 ,-1 , 0
       0    .055       0  245.39      .1       0  423.58     .05       0
  455.29      .1       0   532.9    .045       0   552.3      .1       0
#XS Ineff= 2 , 0
          478.95 2187.78
Permanent Ineff=
       F       F
Bank Sta=532.9,552.3
XS Rating Curve= 0 ,0
Exp/Cntr=0.3,0.1

Type RM Length L Ch R = 1 ,57      ,,,
XS GIS Cut Line= 4
2111759.26706098359448.7507718592111738.72387814358984.158790752
2111751.36583681358898.8255697322111775.06950932358652.307375675
#Sta/Elev= 30
       0    2209    56.4 2200.31   102.4  2194.8   118.8 2193.77   138.5 2193.68
   148.4 2193.01   178.7 2194.14   220.6 2193.96   250.2 2191.27   299.5 2188.47
   335.2 2188.32   355.3 2186.77   367.4 2186.46   440.7 2186.42   576.4 2185.38
   606.5 2183.23   618.5 2183.59     629 2185.11   633.5 2185.19   645.4 2183.98
   652.1 2183.33   667.2 2183.17   675.1 2183.26   680.7 2183.87     685 2185.23
   691.6 2190.77   694.9 2192.74   704.8 2196.01   721.3 2199.63     799  2202.4
#Mann= 5 ,-1 , 0
       0     .05       0   250.2      .1       0   367.4     .05       0
   645.4    .045       0   680.7     .05       0
Bank Sta=645.4,680.7
XS Rating Curve= 0 ,0
Exp/Cntr(USF)=0,0
Exp/Cntr=0.3,0.1
LCMann Table=0

Chan Stop Cuts=-1
Use User Specified Reach Order=0
Composite Channel Slope=5